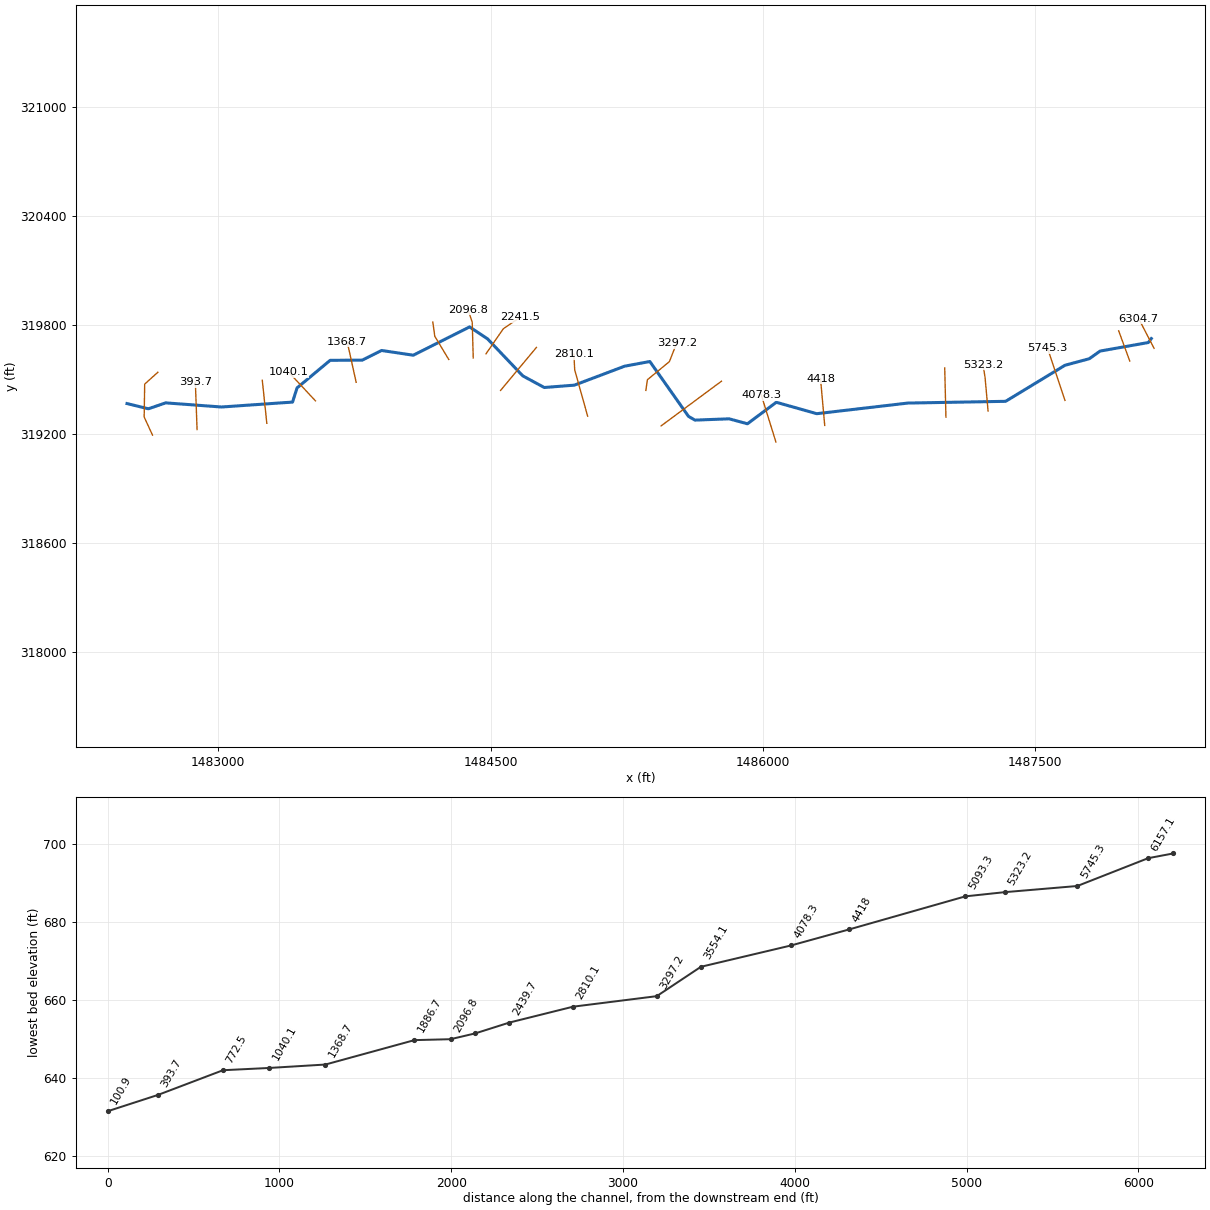
--- LongRn.prj (project) ---

Proj Title=LongRn
Current Plan=p01
Default Exp/Contr=0,0
English Units
Geom File=g01
Flow File=f01
Plan File=p01
BEGIN DESCRIPTION:
AMEC Environment & Infrastructure, 2013
Projection: NAD 1983 State Plane West Virginia North FIPS 4701 (US Feet)
Vertical Datum: NAVD 1988
END DESCRIPTION:
DSS Export Rating Curves= 0
DSS Export Rating Curve Sorted= 0
DSS Export Volume Flow Curves= 0
DXF OffsetX= 0
DXF OffsetY= 0
DXF ScaleX= 0
DXF ScaleY= 0

--- LongRn.p01 (plan) ---

Plan Title=Floodplain
Program Version=4.00
Geom File=g01
Flow File=f01
K Sum by GR=0
Std Step Tol=0.01
Critical Tol=0.01
Num of Std Step Trials=20
Max Error Tol=0.3
Flow Tol Ratio=0.001
Split Flow NTrial=30
Split Flow Tol=0.02
Split Flow Ratio=0.02
Log Output Level=0
Friction Slope Method=1
Unsteady Friction Slope Method=2
Unsteady Bridges Friction Slope Method=1
Global Log Level=0
CheckData=False
Run HTab=0
Run UNet=0
Run PostProcess=0
UNET Theta=0
UNET Theta Warmup=0
UNET ZTol=0
UNET ZSATol=0
UNET MxIter=0
UNET MaxInSteps=0
UNET DtIC=0
UNET DtMin=0
UNET MaxCRTS=0
UNET WFStab=0
UNET SFStab=0
UNET WFX=0
UNET SFX=0
UNET DSS MLevel=0
UNET DZMax Abort=0
UNET Convert EG Bridges=0
UNET Use Existing IB Tables=0
UNET Froude Limit=0
UNET Froude Power=0
Write IC File=0
Echo Input=False
Echo Output=False
Write Detailed=0

--- LongRn.f01 (steady flow) ---

Flow Title=USGS Regress. Eqn. (2010) - Western-Plateaus
Program Version=4.10
Number of Profiles= 1
Profile Names=P100yr
River Rch & RM=LongRn,Main            ,6304.7
     995
River Rch & RM=LongRn,Main            ,5093.3
    1028
River Rch & RM=LongRn,Main            ,3554.1
    1077
River Rch & RM=LongRn,Main            ,393.7
    1162
River Rch & RM=LongRn,Main            ,100.9
    1165
Boundary for River Rch & Prof#=LongRn,Main            , 1
Up Type= 0
Dn Type= 3
Dn Slope=0.01587
DSS Import GetInterval= 0
DSS Import GetPeak= 0
DSS Import FillOption= 0

--- LongRn.g01 (geometry) ---

Geom Title=USGS 3m DEM
Program Version=4.10

River Reach=LongRn          ,Main
Reach XY= 30
     1488140.181      319725.866     1488123.708      319704.135
     1487857.734      319657.018     1487798.055        319614.7
     1487664.591      319578.893     1487337.327       319380.16
     1486798.706      319370.559     1486296.737      319312.053
      1486073.88        319374.9     1485914.966      319256.476
     1485813.977      319283.799     1485625.838       319276.64
     1485590.422      319297.126     1485377.265      319599.509
     1485238.612      319573.768     1484961.683      319469.301
     1484795.668       319456.28     1484677.395      319520.299
     1484483.007      319724.462     1484384.099      319790.051
     1484074.097      319634.231       1483899.4      319660.273
     1483793.064      319607.104     1483616.197      319606.019
     1483433.906       319454.11     1483408.949      319375.985
     1483017.239      319348.858     1482710.164      319371.644
     1482614.678      319339.092     1482497.059      319367.797

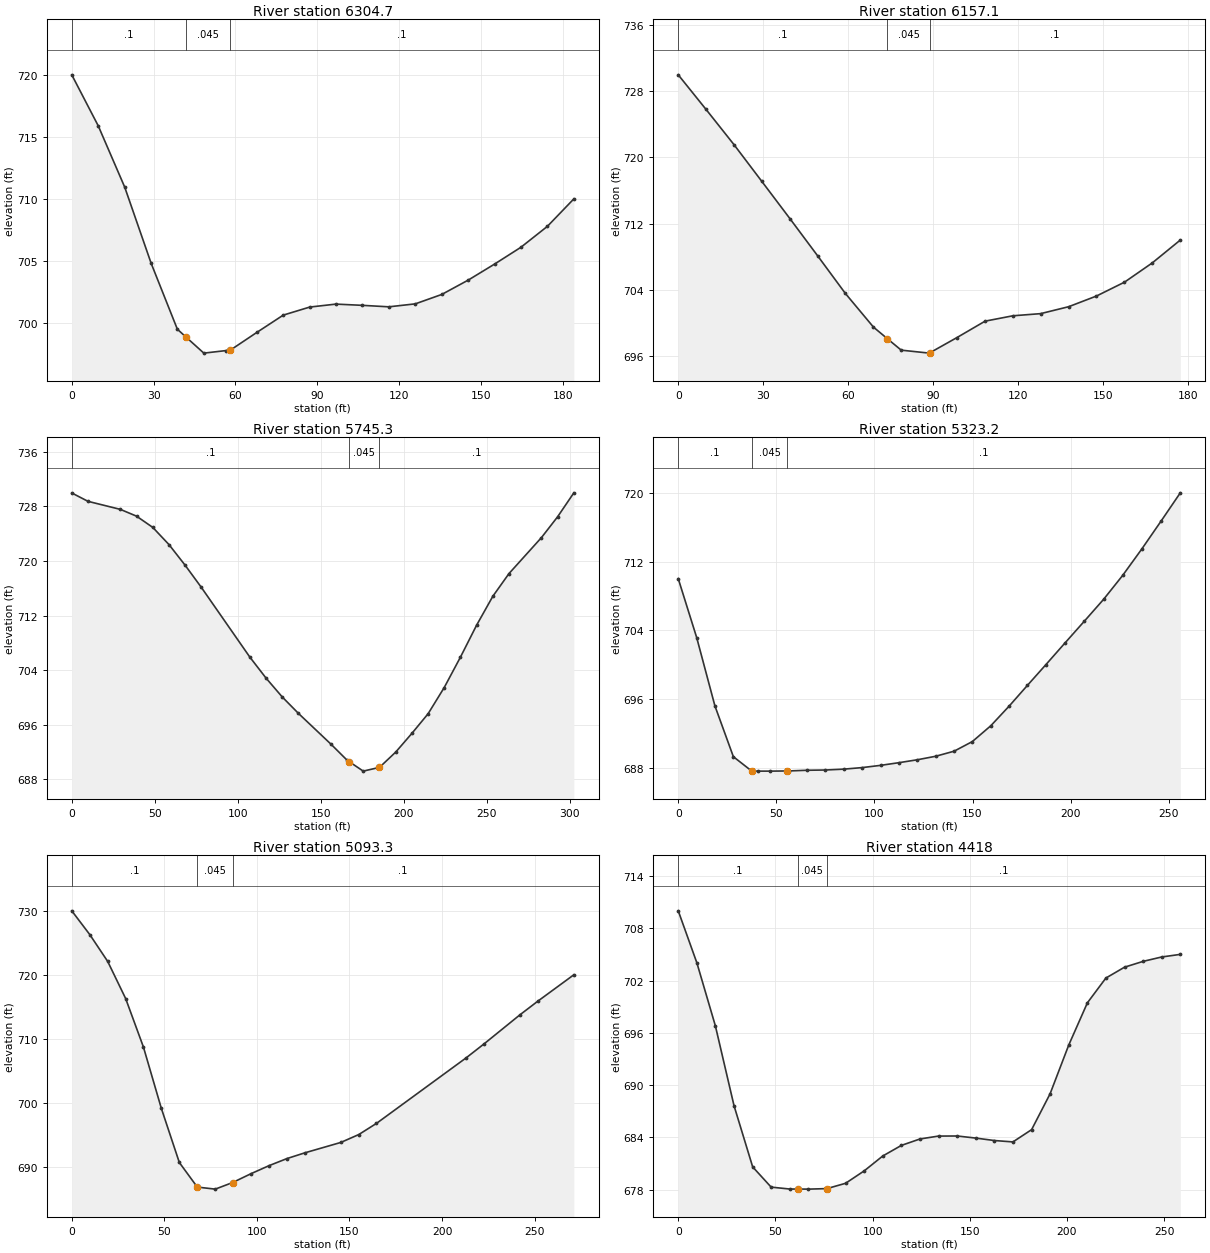
Type RM Length L Ch R = 1 ,6304.7  ,150.4,147.6,144.9
XS GIS Cut Line= 2
     1488155.086      319671.987     1488070.533      319835.435
#Sta/Elev= 22
       0  720.02     9.7   715.9    19.4  710.95    29.1  704.79    38.7  699.47
    41.7  698.87    48.4  697.54    56.7  697.75    58.1  697.78    67.8  699.21
    77.5  700.61    87.2  701.26    96.8   701.5   106.5   701.4   116.2  701.28
   125.9  701.52   135.6  702.28   145.3  703.44     155  704.74   164.6  706.09
   174.3  707.78     184     710
#Mann= 3 , 0 , 0
       0      .1       0    41.7    .045       0    58.1      .1       0
Bank Sta=41.7,58.1
XS Rating Curve= 0 ,0
Exp/Cntr=0.3,0.1

Type RM Length L Ch R = 1 ,6157.1  ,412.6,411.8,410.8
XS GIS Cut Line= 2
     1488021.166      319602.194     1487960.145      319768.503
#Sta/Elev= 21
       0     730     9.8  725.82    19.7  721.54    29.5   717.1    39.4   712.6
    49.2  708.09      59  703.53    68.9  699.46    73.8  698.06    78.7  696.67
    88.6  696.31    88.8  696.35    98.4   698.2   108.3  700.18   118.1  700.83
   127.9  701.09   137.8  701.93   147.6  703.22   157.5   704.9   167.3  707.23
   177.2     710
#Mann= 3 , 0 , 0
       0      .1       0    73.8    .045       0    88.8      .1       0
Bank Sta=73.8,88.8
XS Rating Curve= 0 ,0
Exp/Cntr=0.3,0.1

Type RM Length L Ch R = 1 ,5745.3  ,427.4,422.1,416.7
XS GIS Cut Line= 2
     1487664.243      319385.273     1487568.411      319672.174
#Sta/Elev= 28
       0  729.98     9.8  728.75    29.3  727.57      39  726.58    48.8  724.93
    58.6   722.4    68.3  719.38    78.1  716.12   107.3   705.9   117.1  702.81
   126.8  700.06   136.6  697.64   156.1  693.15   165.9  690.78   167.1  690.58
   175.6  689.18   185.4  689.73   195.2  691.98   204.9  694.71   214.7   697.6
   224.4  701.44   234.2  705.91   243.9  710.58   253.7  714.83   263.4  718.15
     283  723.44   292.7  726.48   302.5     730
#Mann= 3 , 0 , 0
       0      .1       0   167.1    .045       0   185.4      .1       0
Bank Sta=167.1,185.4
XS Rating Curve= 0 ,0
Exp/Cntr=0.3,0.1

Type RM Length L Ch R = 1 ,5323.2  ,231.3,229.9,228.4
XS GIS Cut Line= 3
     1487240.697      319326.536     1487223.924      319513.179
     1487212.842      319580.769
#Sta/Elev= 30
       0  710.01     9.4  703.15    18.7  695.19    28.1  689.28    37.5   687.6
    40.5   687.6    46.8   687.6    55.5  687.62    56.2  687.62    65.6   687.7
      75  687.73    84.3  687.83    93.7  688.01   103.1  688.27   112.4  688.58
   121.8  688.92   131.2  689.33   140.6  689.92   149.9  691.04   159.3  692.88
   168.7  695.18     178  697.59   187.4     700   197.2  702.54     207  705.06
   216.8   707.6   226.5  710.38   236.3  713.47   246.1  716.71   255.9     720
#Mann= 3 , 0 , 0
       0      .1       0    37.5    .045       0    55.5      .1       0
Bank Sta=37.5,55.5
XS Rating Curve= 0 ,0
Exp/Cntr=0.3,0.1

Type RM Length L Ch R = 1 ,5093.3  ,673.9,675.3,676.8
XS GIS Cut Line= 2
     1487008.508      319292.977     1487001.784      319564.083
#Sta/Elev= 22
       0  729.99     9.7  726.29    19.4  722.09    29.1  716.29    38.7  708.72
    48.4  699.12    58.1  690.68    67.8  686.84    77.5  686.52    86.9  687.55
    96.8  688.93   106.5  690.18   116.2  691.29   125.9  692.19   145.3  693.81
     155  695.04   164.6  696.79   213.1  707.04   222.8  709.23   242.1  713.75
   251.8  715.89   271.2     720
#Mann= 3 , 0 , 0
       0      .1       0    67.8    .045       0    86.9      .1       0
Bank Sta=67.8,86.9
XS Rating Curve= 0 ,0
Exp/Cntr=0.3,0.1

Type RM Length L Ch R = 1 ,4418    ,335.7,339.6,344.4
XS GIS Cut Line= 2
     1486340.701      319247.487      1486317.57      319504.761
#Sta/Elev= 29
       0     710     9.6  704.02    19.1   696.8    28.7  687.63    38.3   680.6
    47.8  678.28    57.4  678.06    61.5  678.06      67  678.05    76.5  678.11
    86.1  678.72    95.7  680.15   105.2  681.85   114.8  683.07   124.4  683.81
   133.9  684.14   143.5  684.15   153.1  683.91   162.6  683.63   172.2  683.47
   181.8  684.88   191.3  688.99   200.9  694.59   210.5  699.44     220  702.28
   229.6  703.53   239.2   704.2   248.7   704.7   258.3     705
#Mann= 3 , 0 , 0
       0      .1       0    61.5    .045       0    76.5      .1       0
Bank Sta=61.5,76.5
XS Rating Curve= 0 ,0
Exp/Cntr=0.3,0.1

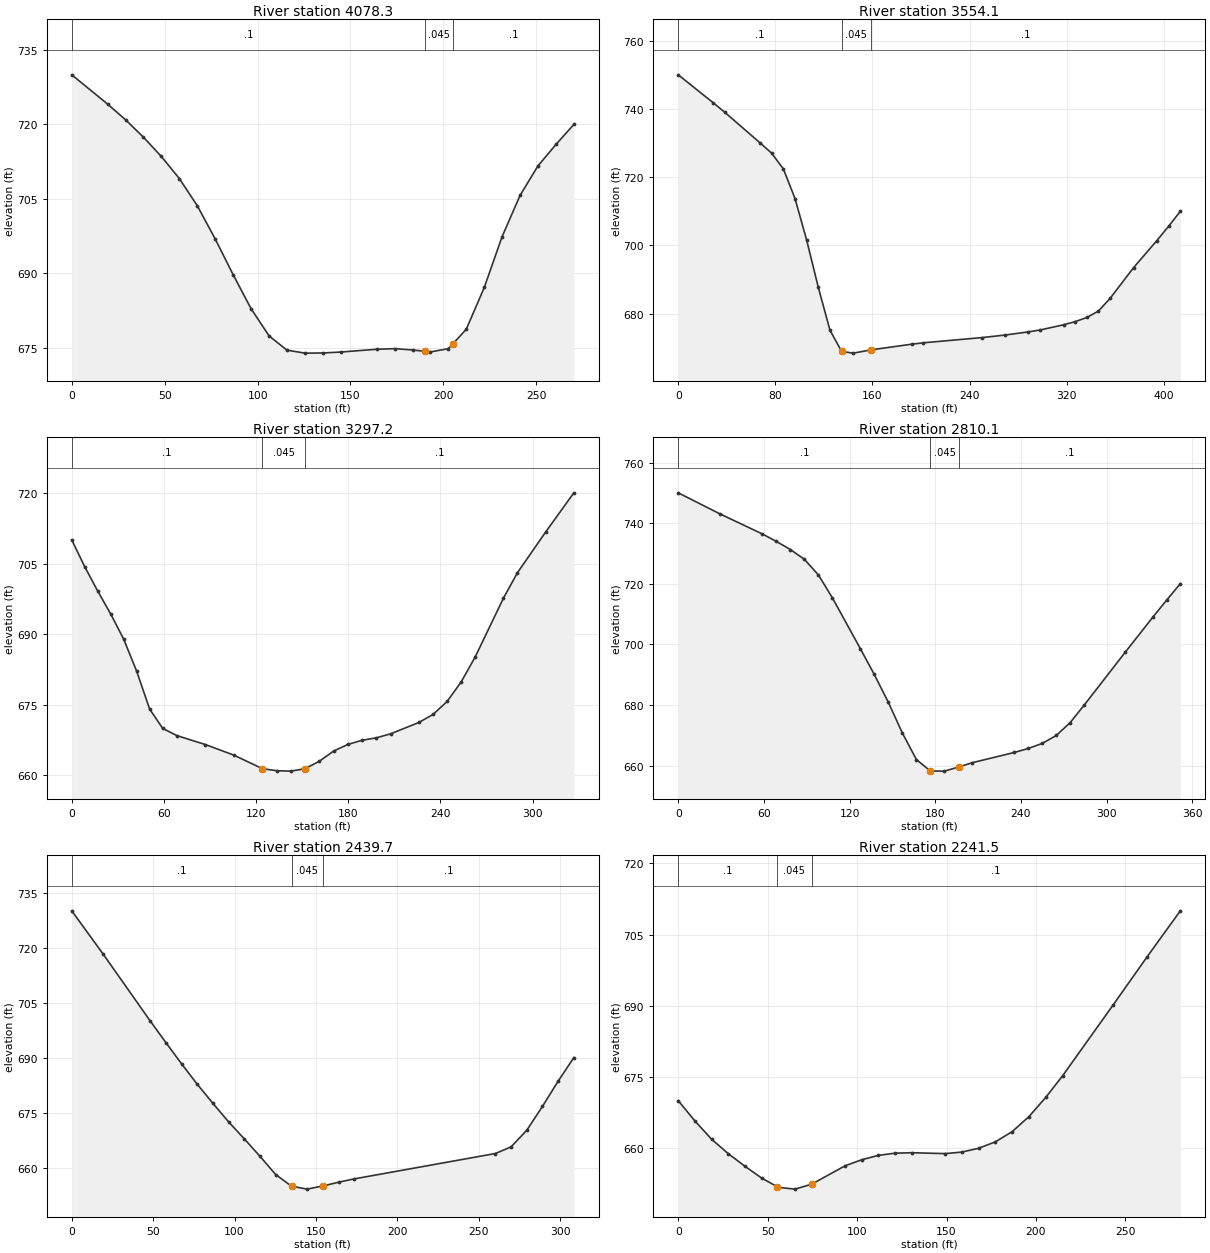
Type RM Length L Ch R = 1 ,4078.3  ,550.8,524.2,496.7
XS GIS Cut Line= 2
     1486071.711      319156.302     1485991.485      319414.333
#Sta/Elev= 29
       0     730    19.3   724.1      29  720.92    38.6  717.42    48.2  713.55
    57.9   709.1    67.6  703.59    77.2  696.92    86.8  689.76    96.5  682.87
   106.2  677.39   115.8  674.52   125.5  673.92   135.1  673.95   144.8  674.14
   164.1   674.7   173.7  674.82   183.4  674.56   190.1  674.28     193  674.16
   202.7  674.82   205.1   675.8   212.3  678.72     222  687.16   231.6   697.4
   241.3  705.74   250.9  711.65   260.6  715.98   270.2     720
#Mann= 3 , 0 , 0
       0      .1       0   190.1    .045       0   205.1      .1       0
Bank Sta=190.1,205.1
XS Rating Curve= 0 ,0
Exp/Cntr=0.3,0.1

Type RM Length L Ch R = 1 ,3554.1  ,255.8,256.9,257.9
XS GIS Cut Line= 2
     1485439.401      319244.885     1485771.817      319490.947
#Sta/Elev= 28
       0     750    28.8  741.82    38.5  738.97    67.3   730.1    76.9  727.06
    86.6  722.44    96.2  713.76   105.8  701.56   115.4  687.71     125  675.16
   134.6  668.94   144.3  668.45   158.9  669.41   192.4  671.07     202  671.48
   250.1     673   269.3  673.75   288.5  674.68   298.2  675.24   317.4  676.75
     327  677.68   336.6  678.89   346.2  680.79   355.9  684.56   375.1   693.5
   394.3  701.44     404  705.65   413.6     710
#Mann= 3 , 0 , 0
       0      .1       0   134.6    .045       0   158.9      .1       0
Bank Sta=134.6,158.9
XS Rating Curve= 0 ,0
Exp/Cntr=0.3,0.1

Type RM Length L Ch R = 1 ,3297.2  ,460.9,487.1,513.3
XS GIS Cut Line= 4
     1485355.297      319440.286     1485363.691      319498.856
     1485485.324      319599.215     1485525.247      319701.716
#Sta/Elev= 30
       0  710.02     8.4  704.34    16.9  699.15    25.4  694.26    33.8  688.94
    42.3   682.1    50.7   674.1    59.2     670    68.4  668.47      87  666.56
   105.6  664.31   124.1  661.44   133.4  661.01   142.6  660.92   151.9  661.43
   161.2  663.02   170.5  665.18   179.8  666.59     189  667.47   198.3  667.99
   207.6  668.84     226  671.25   235.2  672.95   244.4  675.72   253.5  679.84
   262.7  685.18     281  697.61   290.2  703.06   308.5  711.67   326.9  720.01
#Mann= 3 , 0 , 0
       0      .1       0   124.1    .045       0   151.9      .1       0
Bank Sta=124.1,151.9
XS Rating Curve= 0 ,0
Exp/Cntr=0.3,0.1

Type RM Length L Ch R = 1 ,2810.1  ,392.3,370.4,348.6
XS GIS Cut Line= 3
     1485034.783      319298.203     1484963.396      319553.249
     1484958.846      319639.888
#Sta/Elev= 27
       0     750    29.4  743.01    58.9  736.44    68.7  733.98    78.5  731.31
    88.3  728.09    98.1  722.97   107.9  715.42   127.5  698.64   137.3  690.09
   147.1  680.95     157  670.75   166.8  662.02   176.6  658.25   186.4  658.22
   196.8  659.64     206  661.01   235.4  664.38   245.2   665.7     255  667.38
   264.8     670   274.5  674.25   284.1  679.88     313  697.42   332.3  708.96
     342   714.6   351.6  720.04
#Mann= 3 , 0 , 0
       0      .1       0   176.6    .045       0   196.8      .1       0
Bank Sta=176.6,196.8
XS Rating Curve= 0 ,0
Exp/Cntr=0.3,0.1

Type RM Length L Ch R = 1 ,2439.7  ,195.9,198.2,200.3
XS GIS Cut Line= 2
     1484554.818      319439.946     1484752.377      319676.875
#Sta/Elev= 23
       0  730.02    19.3  718.22    48.2     700    57.8  694.12    67.5  688.29
    77.1  682.75    86.8   677.5    96.4  672.47     106  667.86   115.7  663.08
   125.3  658.12     135  654.96   135.3  654.93   144.6  654.15   154.2     655
   163.9  656.03   173.5  656.94   260.3  663.86   269.9  665.66   279.6  670.21
   289.2   676.7   298.8  683.55   308.5  690.02
#Mann= 3 , 0 , 0
       0      .1       0   135.3    .045       0   154.2      .1       0
Bank Sta=135.3,154.2
XS Rating Curve= 0 ,0
Exp/Cntr=0.3,0.1

Type RM Length L Ch R = 1 ,2241.5  ,127.9,144.7,159.1
XS GIS Cut Line= 3
     1484474.657      319641.794     1484570.016      319779.947
     1484663.207      319843.611
#Sta/Elev= 26
       0  670.02     9.3  665.75    18.6  661.91      28  658.84    37.3   656.2
    46.6  653.72    55.2  651.92      56  651.75    65.3  651.38    74.6  652.42
    93.3   656.3   102.6  657.57   111.9  658.49   121.2  658.95   130.6  659.05
   149.2  658.86   158.5  659.18   167.9  659.98   177.3  661.34   186.7  663.49
   196.1  666.67   205.5  670.72   214.9  675.26   243.1  690.15   261.9  700.19
   280.7     710
#Mann= 3 , 0 , 0
       0      .1       0    55.2    .045       0    74.6      .1       0
Bank Sta=55.2,74.6
XS Rating Curve= 0 ,0
Exp/Cntr=0.3,0.1

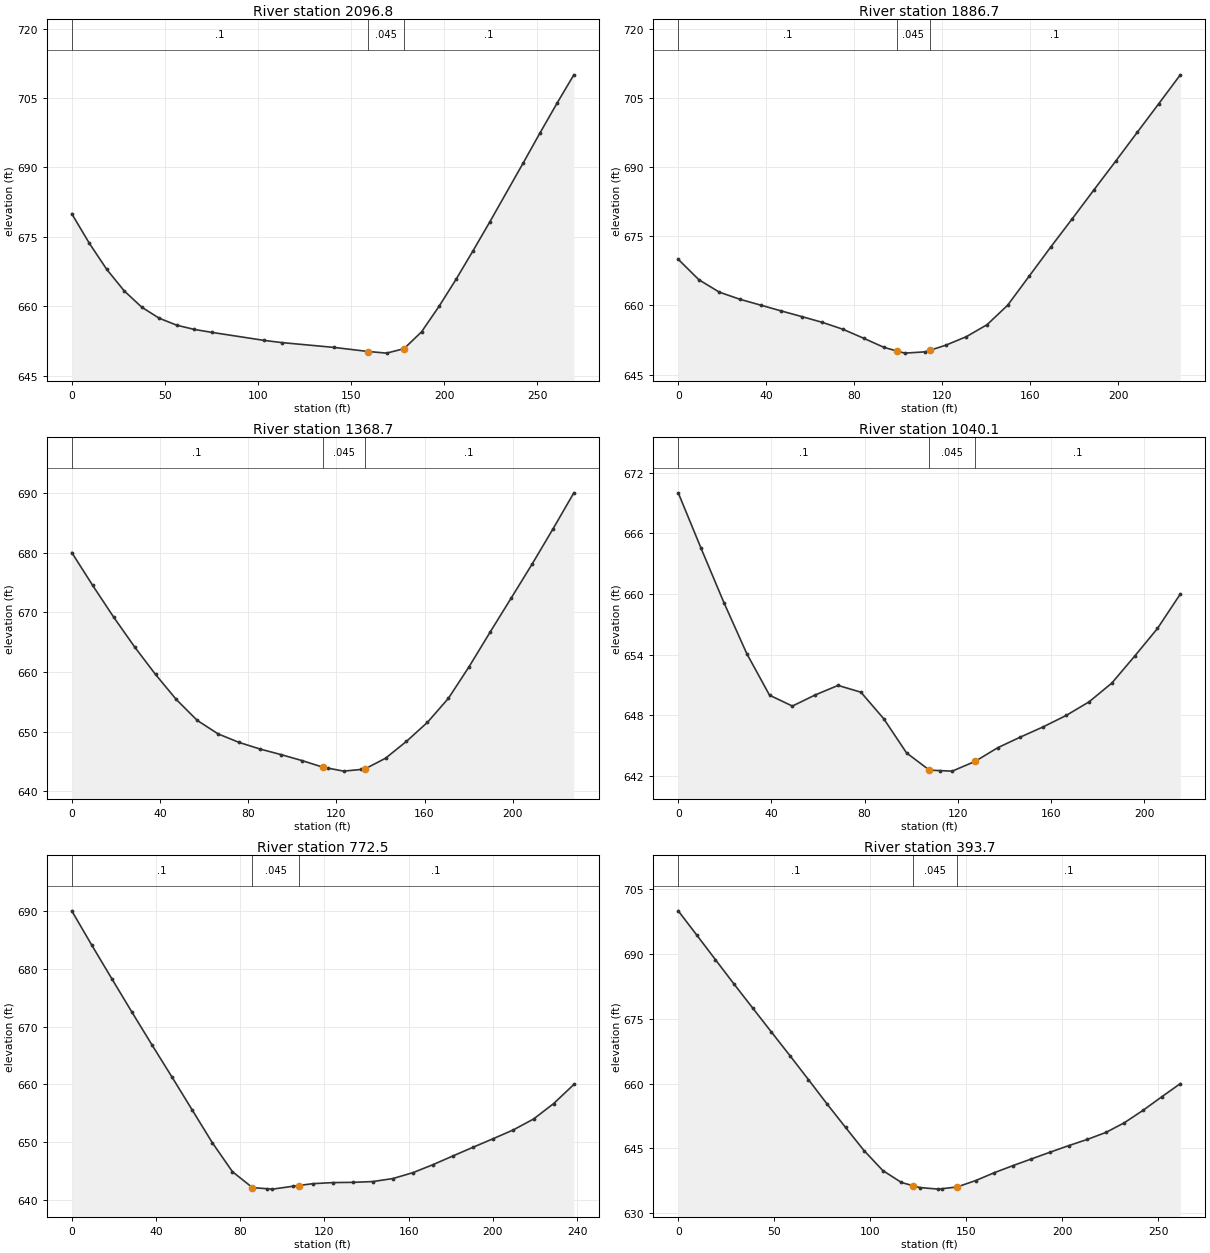
Type RM Length L Ch R = 1 ,2096.8  ,200.8,210.1,221.7
XS GIS Cut Line= 3
     1484404.461        319618.9      1484398.82      319816.055
     1484375.761      319884.647
#Sta/Elev= 24
       0     680     9.4  673.63    18.8  667.96    28.2  663.31    37.6   659.8
      47  657.41    56.4  655.91    65.8     655    75.1  654.37   103.3  652.63
   112.7  652.16   140.9  651.11   159.2  650.23   169.1  649.88   178.4  650.84
   187.8  654.47   197.2  659.98   206.3  665.79   215.3  671.88   224.4  678.18
   242.5  691.03   251.5   697.5   260.6  703.89   269.6     710
#Mann= 3 , 0 , 0
       0      .1       0   159.2    .045       0   178.4      .1       0
Bank Sta=159.2,178.4
XS Rating Curve= 0 ,0
Exp/Cntr=0.3,0.1

Type RM Length L Ch R = 1 ,1886.7  ,525.2,518,510.8
XS GIS Cut Line= 3
     1484269.573      319610.658     1484192.434      319738.892
     1484181.765      319816.576
#Sta/Elev= 27
       0  669.99     9.4  665.55    18.7  662.86    28.1  661.31    37.4  660.06
    46.8  658.79    56.1  657.57    65.5  656.31    74.8  654.82    84.2  652.88
    93.5  650.88    99.3  650.11   102.9  649.64   112.2  649.92   114.3  650.24
   121.6  651.37   130.9  653.21   140.3  655.81   149.6     660   159.4  666.31
   169.2  672.63     179  678.78   188.8  685.01   198.7  691.25   208.5  697.51
   218.3  703.73   228.1     710
#Mann= 3 , 0 , 0
       0      .1       0    99.3    .045       0   114.3      .1       0
Bank Sta=99.3,114.3
XS Rating Curve= 0 ,0
Exp/Cntr=0.3,0.1

Type RM Length L Ch R = 1 ,1368.7  ,316.2,328.5,341
XS GIS Cut Line= 2
     1483759.364      319485.224     1483710.205      319707.537
#Sta/Elev= 27
       0     680     9.5  674.48      19  669.18    28.5  664.19      38  659.57
    47.4  655.38    56.9  651.88    66.4  649.61    75.9  648.19    85.4  647.08
    94.9  646.15   104.4  645.15   113.8  644.05   116.2  643.88   123.3  643.38
   131.2  643.66   132.8  643.72   142.3  645.54   151.8  648.37   161.3  651.55
   170.8  655.57   180.2  660.88   189.7  666.65   199.2  672.32   208.7  678.02
   218.2  683.93   227.7     690
#Mann= 3 , 0 , 0
       0      .1       0   113.8    .045       0   132.8      .1       0
Bank Sta=113.8,132.8
XS Rating Curve= 0 ,0
Exp/Cntr=0.3,0.1

Type RM Length L Ch R = 1 ,1040.1  ,283.5,267.6,251.3
XS GIS Cut Line= 2
     1483535.295       319382.68      1483388.17       319540.16
#Sta/Elev= 24
       0     670     9.8  664.52    19.6  659.16    29.4  654.12    39.2     650
      49  648.93    58.8  650.03    68.6  650.97    78.4   650.3    88.2  647.68
      98   644.3   107.8   642.6   112.4  642.55   117.6   642.5   127.4  643.46
   137.1  644.81   146.9  645.87   156.7  646.88   166.5     648   176.3  649.34
   186.1   651.2   195.9  653.86   205.7   656.6   215.5     660
#Mann= 3 , 0 , 0
       0      .1       0   107.8    .045       0   127.4      .1       0
Bank Sta=107.8,127.4
XS Rating Curve= 0 ,0
Exp/Cntr=0.3,0.1

Type RM Length L Ch R = 1 ,772.5   ,380.4,378.8,377.3
XS GIS Cut Line= 2
     1483267.239      319259.181     1483242.283      319496.217
#Sta/Elev= 28
       0     690     9.5  684.07    19.1  678.22    28.6  672.48    38.1  666.83
    47.7  661.22    57.2  655.59    66.7  649.96    76.3  644.93    85.8  642.18
    92.7  641.99    95.3  641.92   104.9  642.41   107.7  642.54   114.4  642.86
   123.9  643.05   133.5  643.09     143  643.23   152.5  643.75   162.1  644.78
   171.6  646.16   181.1  647.67   190.7  649.18   200.2  650.65   209.7  652.16
   219.3  654.04   228.8   656.7   238.4     660
#Mann= 3 , 0 , 0
       0      .1       0    85.8    .045       0   107.7      .1       0
Bank Sta=85.8,107.7
XS Rating Curve= 0 ,0
Exp/Cntr=0.3,0.1

Type RM Length L Ch R = 1 ,393.7   ,293.9,292.7,291.6
XS GIS Cut Line= 2
     1482882.936      319224.755     1482873.539      319485.971
#Sta/Elev= 30
       0     700     9.7  694.36    19.4  688.68      29  683.08    38.7  677.54
    48.4  672.01    58.1  666.51    67.8  660.93    77.4  655.34    87.1  649.87
    96.8  644.47   106.5  639.89   116.2  637.12   122.2  636.38   125.8  635.94
   135.5  635.58   137.2  635.67   145.2  636.08   154.9  637.57   164.6  639.39
   174.3  641.03   183.9  642.57   193.6  644.13   203.3  645.65     213  647.09
   222.7  648.71   232.3  650.96     242  653.82   251.7  656.94   261.4     660
#Mann= 3 , 0 , 0
       0      .1       0   122.2    .045       0   145.2      .1       0
Bank Sta=122.2,145.2
XS Rating Curve= 0 ,0
Exp/Cntr=0.3,0.1

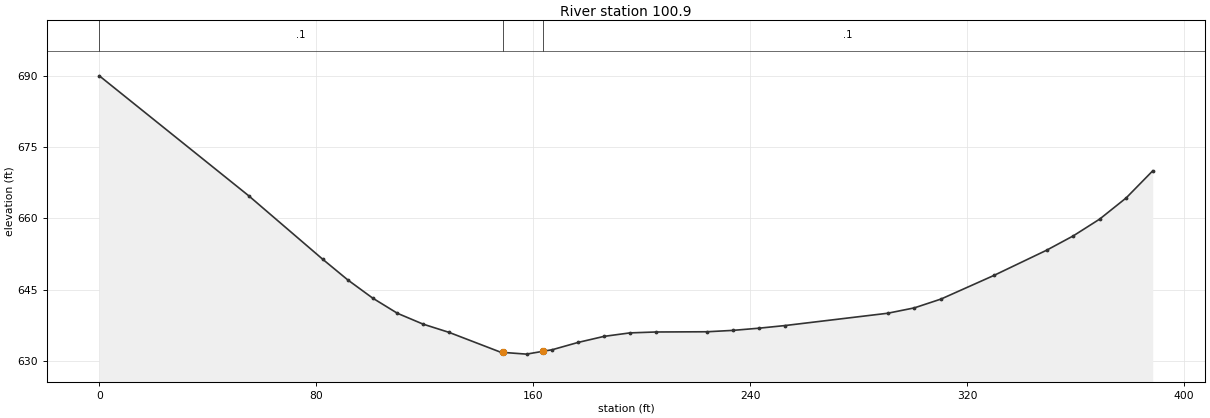
Type RM Length L Ch R = 1 ,100.9   ,112.8,100.9,89
XS GIS Cut Line= 4
     1482637.319      319194.158     1482591.532      319294.097
     1482594.325      319474.885     1482666.846      319540.262
#Sta/Elev= 30
       0     690      55  664.78    82.4  651.36    91.6  647.03   100.8  643.19
   109.9     640   119.4  637.71     129  635.97     148   631.8   148.7  631.77
   157.5   631.4   163.7  632.01     167  632.33   176.5  633.86   186.1  635.14
   195.6  635.87   205.1  636.06   224.1  636.11   233.6   636.4   243.2  636.86
   252.7  637.41   290.7  640.01   300.5  641.14   310.3  642.99   329.8  647.96
   349.3  653.29   359.1   656.3   368.8  659.82   378.6  664.29   388.4     670
#Mann= 3 , 0 , 0
       0      .1       0   148.7    .045       0   163.7      .1       0
Bank Sta=148.7,163.7
XS Rating Curve= 0 ,0
Exp/Cntr=0.3,0.1

Chan Stop Cuts=-1
Use User Specified Reach Order=0
Composite Channel Slope=5